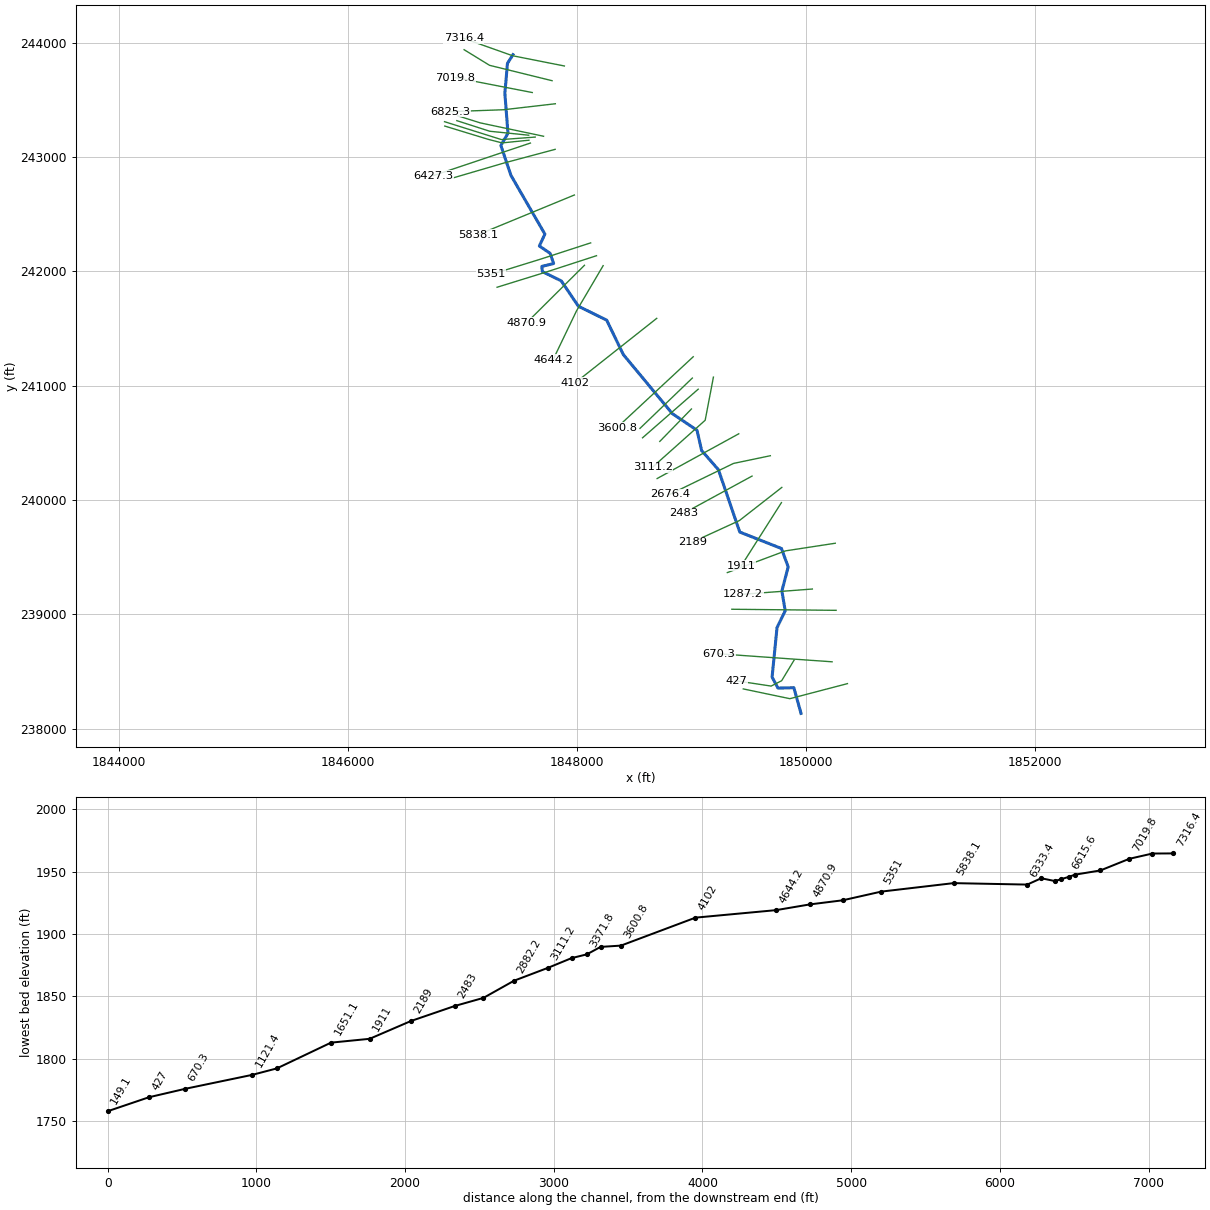
--- MarshFk3.prj (project) ---

Proj Title=MarshFk3
Current Plan=p01
Default Exp/Contr=0,0
English Units
Geom File=g01
Flow File=f01
Plan File=p01
BEGIN DESCRIPTION:
END DESCRIPTION:
DSS Export Rating Curves= 0
DSS Export Rating Curve Sorted= 0
DSS Export Volume Flow Curves= 0
DXF OffsetX= 0
DXF OffsetY= 0
DXF ScaleX= 0
DXF ScaleY= 0

--- MarshFk3.p01 (plan) ---

Plan Title=Floodplain
Program Version=4.00
Geom File=g01
Flow File=f01
K Sum by GR=0
Std Step Tol=0.01
Critical Tol=0.01
Num of Std Step Trials=20
Max Error Tol=0.3
Flow Tol Ratio=0.001
Split Flow NTrial=30
Split Flow Tol=0.02
Split Flow Ratio=0.02
Log Output Level=0
Friction Slope Method=1
Unsteady Friction Slope Method=2
Unsteady Bridges Friction Slope Method=1
Global Log Level=0
CheckData=False
Run HTab=0
Run UNet=0
Run PostProcess=0
UNET Theta=0
UNET Theta Warmup=0
UNET ZTol=0
UNET ZSATol=0
UNET MxIter=0
UNET MaxInSteps=0
UNET DtIC=0
UNET DtMin=0
UNET MaxCRTS=0
UNET WFStab=0
UNET SFStab=0
UNET WFX=0
UNET SFX=0
UNET DSS MLevel=0
UNET DZMax Abort=0
UNET Convert EG Bridges=0
UNET Use Existing IB Tables=0
UNET Froude Limit=0
UNET Froude Power=0
Write IC File=0
Echo Input=False
Echo Output=False
Write Detailed=0

--- MarshFk3.f01 (steady flow) ---

Flow Title=NFF Regression Equation
Program Version=4.00
Number of Profiles=1
Profile Names=P100yr
River Rch & RM=MarshFk3,Main      ,7316.4
     557
River Rch & RM=MarshFk3,Main      ,6427.3
584.7005
River Rch & RM=MarshFk3,Main      ,5838.1
782.7928
River Rch & RM=MarshFk3,Main      ,5092.1
793.4983
River Rch & RM=MarshFk3,Main      ,2676.4
866.6711
River Rch & RM=MarshFk3,Main      ,149.1
945.5749
Boundary for River Rch & Prof#=MarshFk3,Main      ,1
Up Type=0
Dn Type=3
Dn Slope=0.028875

--- MarshFk3.g01 (geometry) ---

Geom Title=USGS 10m DEM
Program Version=4.00

River Reach=MarshFk3        ,Main
Reach XY= 30
      1847440.97      243895.761     1847392.809      243819.338
     1847370.243      243557.413     1847397.264      243208.082
     1847335.503      243100.966     1847423.319       242839.45
     1847719.575      242326.067     1847671.325      242221.846
     1847764.931      242158.156     1847795.811      242068.411
     1847692.555       242043.32      1847697.38      241997.965
     1847862.396      241916.905     1848011.972      241694.954
     1848259.013      241573.363     1848404.263       241272.24
      1848832.47      240755.372     1849047.422      240610.288
     1849087.953      240432.727     1849234.634      240264.816
     1849420.879      239719.588     1849784.687      239575.802
     1849843.552      239414.647     1849788.546      239204.275
     1849817.497      239030.575     1849746.086      238883.894
     1849702.964      238450.968     1849754.464      238354.578
     1849893.101      238358.104     1849955.555       238133.48

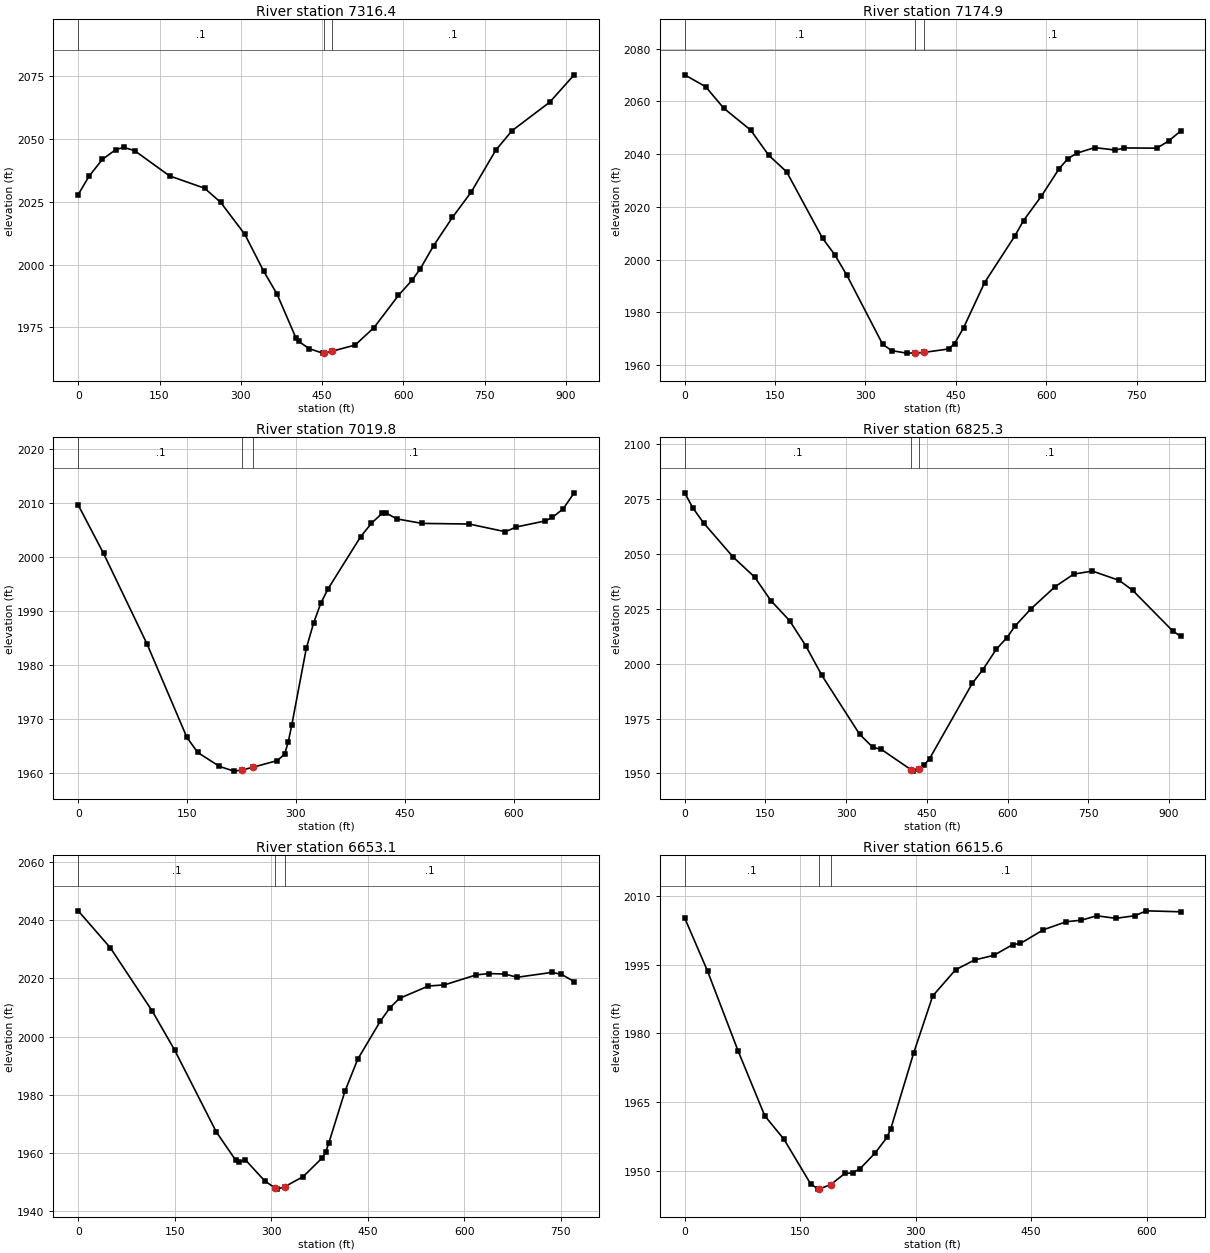
Type RM Length L Ch R = 1 ,7316.4  ,141.2,141.5,145
XS GIS Cut Line= 3
     1847889.747      243796.637     1847437.617       243886.34
     1847009.935      244038.523
#Sta/Elev= 30
       0 2027.85    19.8 2035.13    44.6  2041.9    69.4  2045.8    84.3 2046.67
   104.1 2045.36   168.5 2035.31     233 2030.42   262.7  2024.8   307.3 2012.05
     342  1997.4   366.8  1988.2   401.5 1970.82   406.4  1969.4   426.2 1966.47
     451 1964.69   453.4 1964.73   468.4 1965.47   510.8  1967.9   545.8 1974.89
   590.6 1987.66   615.6 1993.69   630.6 1998.13   655.5 2007.47   690.4 2018.78
   725.3 2028.97   770.2 2045.54   800.2 2053.31     870 2064.72   914.9 2075.59
#Mann= 3 , 0 , 0
       0      .1       0   453.4    .045       0   468.4      .1       0
Bank Sta=453.4,468.4
XS Rating Curve= 0 ,0
Exp/Cntr=0.3,0.1

Type RM Length L Ch R = 1 ,7174.9  ,153.8,155.1,156.3
XS GIS Cut Line= 3
     1847782.496      243667.868     1847236.586      243802.526
     1847014.583      243939.004
#Sta/Elev= 30
       0 2070.08    34.8 2065.58    64.7 2057.46   109.5 2049.12   139.3 2039.63
   169.2 2033.31   228.9 2008.09   248.8 2001.97   268.7 1994.28   328.4 1967.99
   343.3 1965.55   368.2 1964.59   381.9 1964.64   396.9 1964.86   437.9 1966.16
   447.8  1968.2   462.8 1974.22   497.6 1991.31   547.4 2008.85   562.3 2014.86
   591.8 2024.08   621.3 2034.49     636 2038.34   650.8 2040.38   680.3  2042.5
   714.7 2041.56   729.4 2042.36   783.5 2042.29   803.2 2045.04   822.9 2048.76
#Mann= 3 , 0 , 0
       0      .1       0   381.9    .045       0   396.9      .1       0
Bank Sta=381.9,396.9
XS Rating Curve= 0 ,0
Exp/Cntr=0.3,0.1

Type RM Length L Ch R = 1 ,7019.8  ,187.7,194.6,201.5
XS GIS Cut Line= 2
     1847609.373      243564.445     1846938.456      243694.965
#Sta/Elev= 30
       0  2009.6    34.9 2000.65    94.8 1983.91   149.7 1966.64   164.6 1963.83
   194.6 1961.25   214.5 1960.37   226.3 1960.59   241.3 1961.11   274.4 1962.32
   284.4  1963.5   289.4 1965.72   294.4 1968.95   314.3 1983.06   324.3 1987.72
   334.3 1991.43   344.2 1994.07   389.1 2003.71   404.1 2006.23   419.1 2008.09
   424.1 2008.15     439 2007.04     474  2006.2   538.8 2006.09   588.7 2004.66
   603.7 2005.54   643.6 2006.66   653.6 2007.31   668.5 2008.92   683.5 2011.86
#Mann= 3 , 0 , 0
       0      .1       0   226.3    .045       0   241.3      .1       0
Bank Sta=226.3,241.3
XS Rating Curve= 0 ,0
Exp/Cntr=0.3,0.1

Type RM Length L Ch R = 1 ,6825.3  ,179.4,172.1,164.9
XS GIS Cut Line= 3
     1847810.823      243466.223     1847358.979      243413.869
     1846892.604      243397.355
#Sta/Elev= 30
       0  2077.8      15 2071.01      35 2064.13      90 2048.55     130 2039.42
     160 2028.75   194.9 2019.58   224.9 2008.17   254.9 1994.63   324.9 1967.88
   349.9  1961.8   364.9 1961.02     420 1951.76   424.9 1951.03     435 1952.21
   444.9 1953.84   454.9 1956.65   534.3 1990.97   554.2  1997.3     579 2006.55
   598.8 2011.86   613.7 2017.06   643.5 2024.98   688.2 2035.03     723 2040.79
   757.7 2042.15   807.4  2037.9   832.2 2033.43   906.6 2014.94   921.5 2012.43
#Mann= 3 , 0 , 0
       0      .1       0     420    .045       0     435      .1       0
Bank Sta=420,435
XS Rating Curve= 0 ,0
Exp/Cntr=0.3,0.1

Type RM Length L Ch R = 1 ,6653.1  ,35.2,37.6,40.1
XS GIS Cut Line= 3
     1847707.835      243182.045     1847155.988      243298.826
     1846959.064      243360.651
#Sta/Elev= 30
       0 2043.22    49.9 2030.53   114.8 2008.87   149.8 1995.39   214.6 1967.24
   244.6 1957.58   249.6 1956.86   259.6 1957.72   289.5  1950.5   305.7 1948.02
   309.5 1947.62   320.7 1948.43   349.4 1951.91   379.4  1958.4   384.4 1960.26
   389.4 1963.52   414.3 1981.19   434.3 1992.27   469.2 2005.24   484.2  2009.9
   499.2 2013.16   544.1 2017.39     569 2017.78   618.1  2021.2   637.8 2021.67
   662.4 2021.51     682  2020.4   736.1 2022.07   750.8  2021.4   770.5 2018.91
#Mann= 3 , 0 , 0
       0      .1       0   305.7    .045       0   320.7      .1       0
Bank Sta=305.7,320.7
XS Rating Curve= 0 ,0
Exp/Cntr=0.3,0.1

Type RM Length L Ch R = 1 ,6615.6  ,53.6,58.4,65
XS GIS Cut Line= 3
      1847578.69      243191.106     1847238.406      243225.681
     1846950.893      243318.486
#Sta/Elev= 30
       0 2005.17    29.7 1993.57    69.4 1976.14   104.1 1961.96   128.9 1956.88
   163.6 1947.12   173.5 1945.98   174.7 1946.01   189.7 1946.97   208.2 1949.42
   218.1 1949.51     228 1950.46   247.8 1953.95   262.7 1957.26   267.7 1959.13
   297.4 1975.67   322.2 1988.15   351.9 1993.86   376.7    1996   401.5    1997
   426.2 1999.36   436.1  1999.6   465.9 2002.58   495.6 2004.34   515.4 2004.68
   535.2 2005.64     560 2005.08   584.7 2005.65   599.6 2006.72   644.2 2006.51
#Mann= 3 , 0 , 0
       0      .1       0   174.7    .045       0   189.7      .1       0
Bank Sta=174.7,189.7
XS Rating Curve= 0 ,0
Exp/Cntr=0.3,0.1

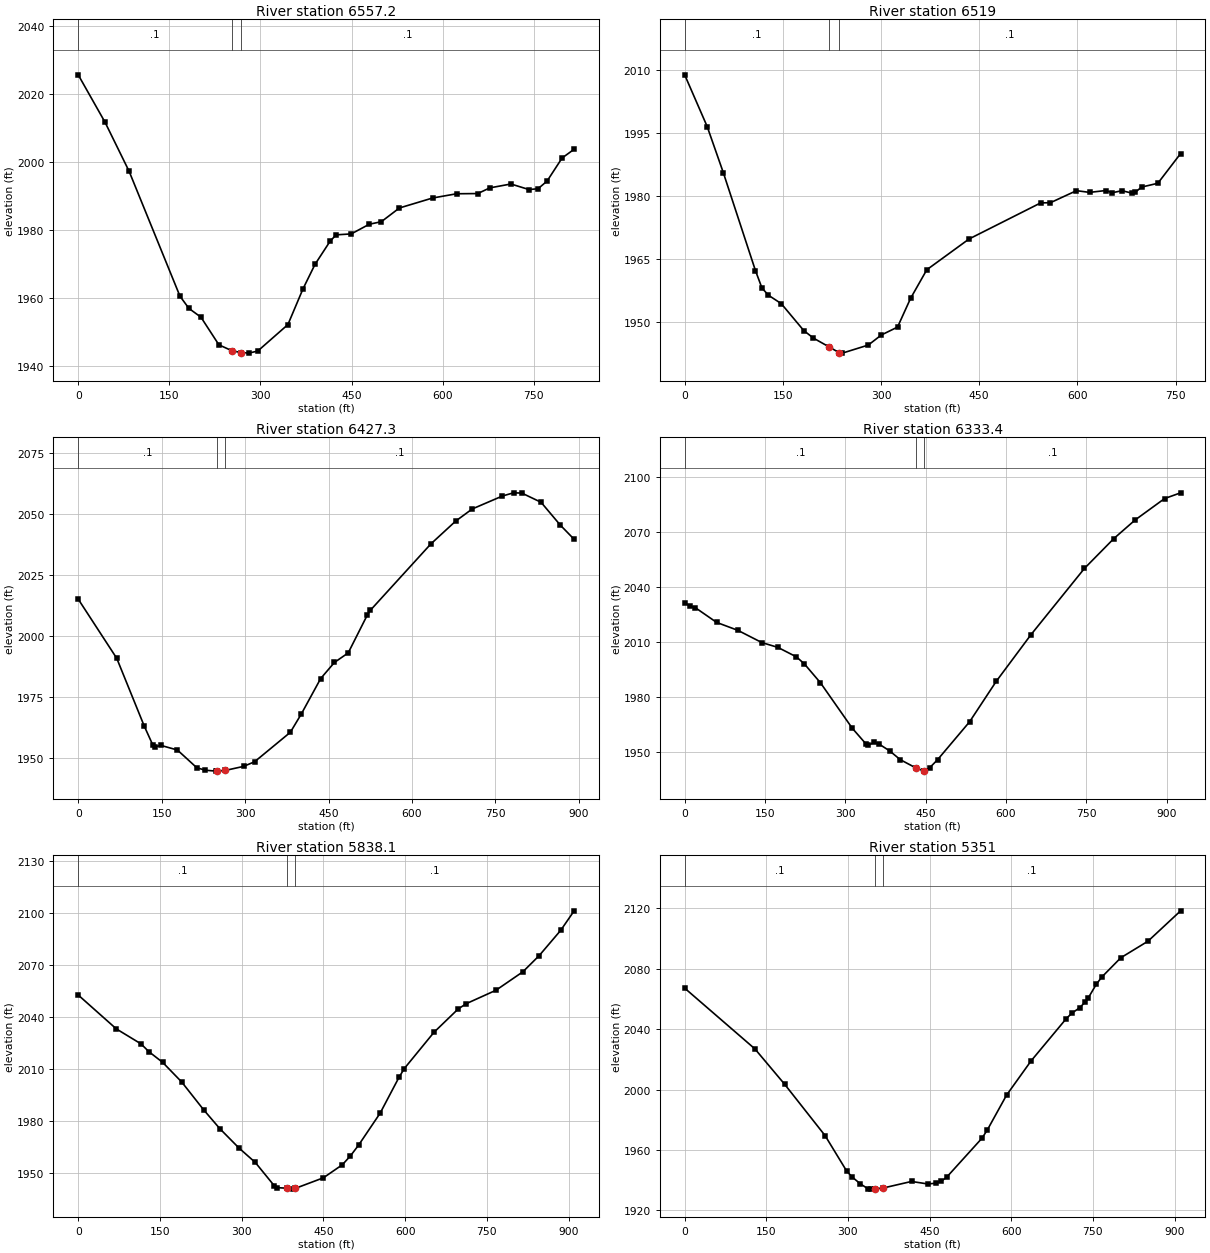
Type RM Length L Ch R = 1 ,6557.2  ,34.5,38.2,31.3
XS GIS Cut Line= 3
     1847635.101      243174.729     1847340.309      243152.893
     1846843.531      243309.387
#Sta/Elev= 30
       0 2025.65    44.3 2011.67    83.8  1997.3   167.5  1960.6   182.3    1957
     202 1954.44   231.6 1946.31   252.8 1944.59   267.8 1944.04   280.8 1943.87
   295.6 1944.49   345.2 1952.26     370 1962.75   389.8 1969.95   414.6 1976.74
   424.6 1978.63   449.4  1978.9   479.1 1981.74     499 1982.49   528.7 1986.52
   583.3 1989.45     623  1990.7   657.7 1990.76   677.6 1992.43   712.3 1993.57
     742 1991.94   756.9 1992.17   771.8 1994.42   796.6 2001.22   816.4 2003.78
#Mann= 3 , 0 , 0
       0      .1       0   252.8    .045       0   267.8      .1       0
Bank Sta=252.8,267.8
XS Rating Curve= 0 ,0
Exp/Cntr=0.3,0.1

Type RM Length L Ch R = 1 ,6519    ,89.3,91.7,102.6
XS GIS Cut Line= 4
      1847580.51      243147.434     1847345.768      243123.778
     1847225.668      243154.713      1846845.35      243271.173
#Sta/Elev= 30
       0 2008.89    34.4 1996.55      59 1985.58   108.1 1962.22     118 1958.08
   127.8 1956.35   147.5 1954.34   181.9 1947.92   196.6 1946.12   220.9 1943.99
   235.9 1942.65   240.9 1942.53   280.6 1944.46   300.4 1946.85   325.2 1948.74
   345.1 1955.58   369.9 1962.41   434.5 1969.75   543.9 1978.35   558.8  1978.4
   598.6 1981.27   618.5 1980.86   643.4  1981.3   653.3 1980.78   668.2 1981.26
   683.1 1980.69   688.1 1980.85     698 1982.12   722.9 1983.03   757.7 1990.12
#Mann= 3 , 0 , 0
       0      .1       0   220.9    .045       0   235.9      .1       0
Bank Sta=220.9,235.9
XS Rating Curve= 0 ,0
Exp/Cntr=0.3,0.1

Type RM Length L Ch R = 1 ,6427.3  ,95.3,93.9,92.5
XS GIS Cut Line= 3
     1847593.344       243122.51     1847128.712      242966.205
     1846748.401      242838.572
#Sta/Elev= 30
       0 2015.09    69.3 1990.88   118.8 1963.12   133.7 1955.65   138.6 1954.74
   148.6 1955.29   178.3  1953.4   212.9  1946.2   227.8 1945.16   247.6 1944.77
   249.2 1944.78   264.2 1945.05   297.1  1946.7   316.9 1948.58   381.3 1960.65
   401.1 1968.17   435.8 1982.62   460.5  1989.2   485.3 1993.11   519.9 2008.72
   524.9 2010.48   633.8 2037.65   678.4 2046.98   708.1 2051.94   762.6 2057.26
   782.4 2058.55   797.3 2058.45   831.9 2054.69   866.6 2045.33   891.4 2039.54
#Mann= 3 , 0 , 0
       0      .1       0   249.2    .045       0   264.2      .1       0
Bank Sta=249.2,264.2
XS Rating Curve= 0 ,0
Exp/Cntr=0.3,0.1

Type RM Length L Ch R = 1 ,6333.4  ,492.4,495.3,498.2
XS GIS Cut Line= 3
     1847809.201      243067.406     1847357.943       242946.47
     1846917.562      242817.395
#Sta/Elev= 30
       0 2031.62     9.9 2029.57    19.9 2028.81    59.6 2020.79    99.4 2016.45
   144.1 2009.79     174 2007.17   208.7 2001.99   223.6 1998.13   253.5 1987.88
   313.1 1963.02     338  1954.7   342.9 1953.76   352.9 1955.34   362.8 1954.48
   382.7 1950.74   402.6 1945.94   431.8 1941.43   446.8 1939.71   447.3 1939.69
   457.2 1941.44   472.2 1945.91     532 1966.58   581.9 1988.69   646.8 2014.15
   746.5 2050.22   801.4  2066.5   841.3 2076.67   896.2 2088.32   926.1 2091.44
#Mann= 3 , 0 , 0
       0      .1       0   431.8    .045       0   446.8      .1       0
Bank Sta=431.8,446.8
XS Rating Curve= 0 ,0
Exp/Cntr=0.3,0.1

Type RM Length L Ch R = 1 ,5838.1  ,490.1,487.1,482.8
XS GIS Cut Line= 3
       1847977.1      242668.163     1847556.531      242494.534
     1847135.963      242320.905
#Sta/Elev= 30
       0 2052.87      70 2033.31     115 2024.72     130  2020.1     155 2013.99
     190 2002.64     230 1986.69     260  1975.7     295 1964.58     325 1956.23
     360 1942.71     365 1941.72   383.6 1941.37     395 1940.86   398.6 1941.32
     450 1947.41   484.7 1954.94   499.5 1960.05   514.4 1966.21   553.9 1984.64
   588.5 2005.31   598.4 2010.46   652.8 2031.36   697.3 2044.85   712.2  2047.9
   766.6 2055.63     816 2066.29   845.7 2075.56   885.3 2090.18     910 2101.45
#Mann= 3 , 0 , 0
       0      .1       0   383.6    .045       0   398.6      .1       0
Bank Sta=383.6,398.6
XS Rating Curve= 0 ,0
Exp/Cntr=0.3,0.1

Type RM Length L Ch R = 1 ,5351    ,258.4,258.9,256.4
XS GIS Cut Line= 3
     1848118.996      242249.204     1847685.073      242107.867
     1847250.722      241973.163
#Sta/Elev= 30
       0 2067.15     129 2026.93   183.5 2003.56   257.9 1969.52   297.6 1946.02
   307.6 1942.11   322.4 1937.64   337.3 1934.14   342.3 1934.05   349.8  1934.3
   364.8  1934.8   416.7 1939.13   446.4 1937.49   461.4 1937.94   471.4 1939.28
   481.4 1941.99   546.3 1967.82   556.3 1973.44   591.3 1996.28   636.3 2018.94
   701.2 2047.04   711.2 2050.53   726.2 2054.33   736.2 2058.22   741.2 2060.54
   756.2  2069.7   766.2 2074.47   801.2 2087.27   851.2 2098.26   911.1 2118.36
#Mann= 3 , 0 , 0
       0      .1       0   349.8    .045       0   364.8      .1       0
Bank Sta=349.8,364.8
XS Rating Curve= 0 ,0
Exp/Cntr=0.3,0.1

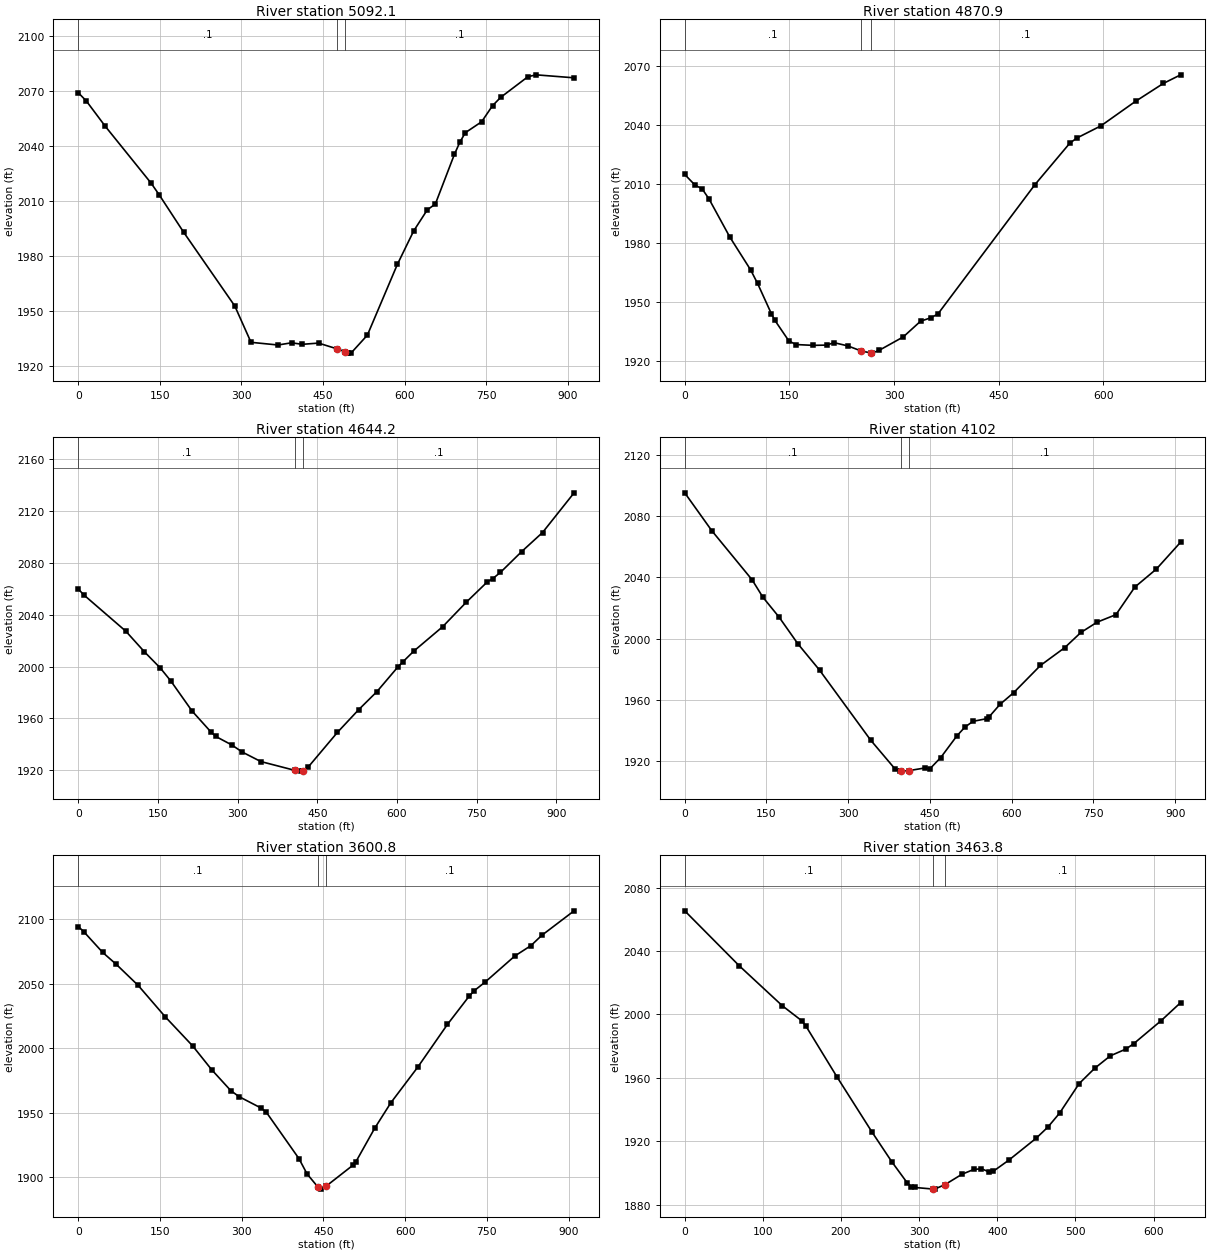
Type RM Length L Ch R = 1 ,5092.1  ,206.7,221.2,234.8
XS GIS Cut Line= 3
      1848170.37      242137.095     1847736.447      241995.758
     1847302.096      241861.054
#Sta/Elev= 30
       0 2069.03    14.9 2064.51    49.6 2050.75   133.9 2019.73   148.8 2013.36
   193.5 1993.07   287.7 1952.77   317.5 1932.98   367.1 1931.52   391.9 1932.72
   411.7 1931.89   441.5 1932.56   474.6 1929.51   489.6 1927.93   496.3 1927.09
   501.3 1927.12   531.3  1936.9   586.3 1975.39   616.3 1993.64   641.3 2005.15
   656.2 2008.36   691.2 2035.42   701.2 2042.04   711.2  2047.2   741.2 2053.17
   761.2 2061.92   776.2 2066.47   826.2 2077.71   841.2 2078.75   911.1 2077.12
#Mann= 3 , 0 , 0
       0      .1       0   474.6    .045       0   489.6      .1       0
Bank Sta=474.6,489.6
XS Rating Curve= 0 ,0
Exp/Cntr=0.3,0.1

Type RM Length L Ch R = 1 ,4870.9  ,222.2,226.7,232.2
XS GIS Cut Line= 2
     1848065.047      242053.164     1847561.286      241551.694
#Sta/Elev= 30
       0 2014.62    14.9 2009.14    24.8 2007.37    34.8 2002.17    64.6 1982.81
    94.4 1966.13   104.4 1959.23   124.3 1943.72   129.2 1940.46   149.1 1930.07
   159.1 1928.16   183.9 1927.74   203.8 1927.87   213.7 1929.13   233.6 1927.48
   252.6 1924.93   267.6 1923.82   268.4 1923.79   278.4 1925.16   313.2 1932.02
     338 1940.01   352.9 1941.78   362.9 1943.69     502 2009.46   551.8 2030.46
   561.7 2033.07   596.5 2039.32   646.2  2051.8     686 2060.89   710.8 2065.27
#Mann= 3 , 0 , 0
       0      .1       0   252.6    .045       0   267.6      .1       0
Bank Sta=252.6,267.6
XS Rating Curve= 0 ,0
Exp/Cntr=0.3,0.1

Type RM Length L Ch R = 1 ,4644.2  ,550.8,542.2,533.5
XS GIS Cut Line= 3
     1848228.201      242049.929     1847995.875      241654.755
     1847790.448      241226.386
#Sta/Elev= 30
       0 2059.98      10 2055.52    89.7 2027.26   124.6 2011.38   154.5 1998.87
   174.4 1988.81   214.3 1965.65   249.1  1949.8   259.1 1945.96     289 1939.45
   308.9 1933.92   343.8  1926.6   407.7  1919.8   418.6  1919.2   422.7 1919.52
   433.5 1922.61   488.1 1949.19   527.7 1966.56   562.3  1980.6   601.9 1999.72
   611.8 2003.86   631.6 2011.85     686 2030.72   730.6 2049.69   770.2  2065.4
   780.1 2067.84   794.9 2072.72   834.5 2088.66   874.1 2103.51   933.5 2134.17
#Mann= 3 , 0 , 0
       0      .1       0   407.7    .045       0   422.7      .1       0
Bank Sta=407.7,422.7
XS Rating Curve= 0 ,0
Exp/Cntr=0.3,0.1

Type RM Length L Ch R = 1 ,4102    ,499.5,501.2,503
XS GIS Cut Line= 3
     1848695.906       241589.09     1848339.259      241306.552
     1847982.613      241024.013
#Sta/Elev= 30
       0  2095.4    49.5 2070.67   123.6 2038.46   143.4 2027.06   173.1 2014.03
   207.7  1996.5   247.3 1979.36   341.2 1933.47   385.8 1914.66   395.6 1913.18
   396.7 1913.18   411.7 1913.52   440.2 1915.22     450 1914.74   469.8 1922.07
   499.5 1936.29   514.4 1942.09   529.2  1945.8   553.9  1947.5   558.9 1948.89
   578.6 1956.91   603.4 1964.48   652.8 1982.38   697.3 1994.02     727 2003.96
   756.7  2010.7   791.3 2015.63   825.9 2033.65   865.5 2045.49     910 2063.08
#Mann= 3 , 0 , 0
       0      .1       0   396.7    .045       0   411.7      .1       0
Bank Sta=396.7,411.7
XS Rating Curve= 0 ,0
Exp/Cntr=0.3,0.1

Type RM Length L Ch R = 1 ,3600.8  ,136.6,137.1,137.5
XS GIS Cut Line= 3
     1849014.738      241253.151     1848681.726      240943.106
     1848348.714       240633.06
#Sta/Elev= 30
       0  2094.3      10 2090.41      45 2074.19      70 2064.93     110 2048.67
     160  2024.2     210 2001.78     245 1983.29     280 1967.12     295 1962.49
     335 1953.73     345  1950.5     405 1914.47     420 1902.52   439.7 1892.49
     445 1890.76   454.7 1892.97   504.5 1909.41   509.4 1911.84     544  1937.9
   573.7 1957.68   623.2 1985.36   677.6 2018.45   717.1 2040.14     727 2044.65
   746.8 2051.25   801.2 2071.45   830.9 2079.53   850.6 2087.43     910 2106.47
#Mann= 3 , 0 , 0
       0      .1       0   439.7    .045       0   454.7      .1       0
Bank Sta=439.7,454.7
XS Rating Curve= 0 ,0
Exp/Cntr=0.3,0.1

Type RM Length L Ch R = 1 ,3463.8  ,93.1,92,90.9
XS GIS Cut Line= 2
     1849006.577      241066.636     1848549.514      240626.277
#Sta/Elev= 30
       0 2065.32      70 2030.53   124.9 2005.42   149.9 1995.91   154.9 1992.76
   194.9  1960.5   239.9 1925.57   264.9 1907.08   284.9  1893.6   289.9 1891.33
   294.8 1890.76   318.3 1889.74   319.8 1889.72   333.3 1892.61   354.8  1899.1
   369.8 1902.11   379.8  1902.6   389.8  1900.5   394.8 1900.95   414.8    1908
   449.8 1921.84   464.8 1928.86   479.8 1937.68   504.8  1956.3   524.7 1965.96
   544.7 1973.82   564.7 1978.11   574.7 1981.51   609.7 1995.99   634.7 2007.39
#Mann= 3 , 0 , 0
       0      .1       0   318.3    .045       0   333.3      .1       0
Bank Sta=318.3,333.3
XS Rating Curve= 0 ,0
Exp/Cntr=0.3,0.1

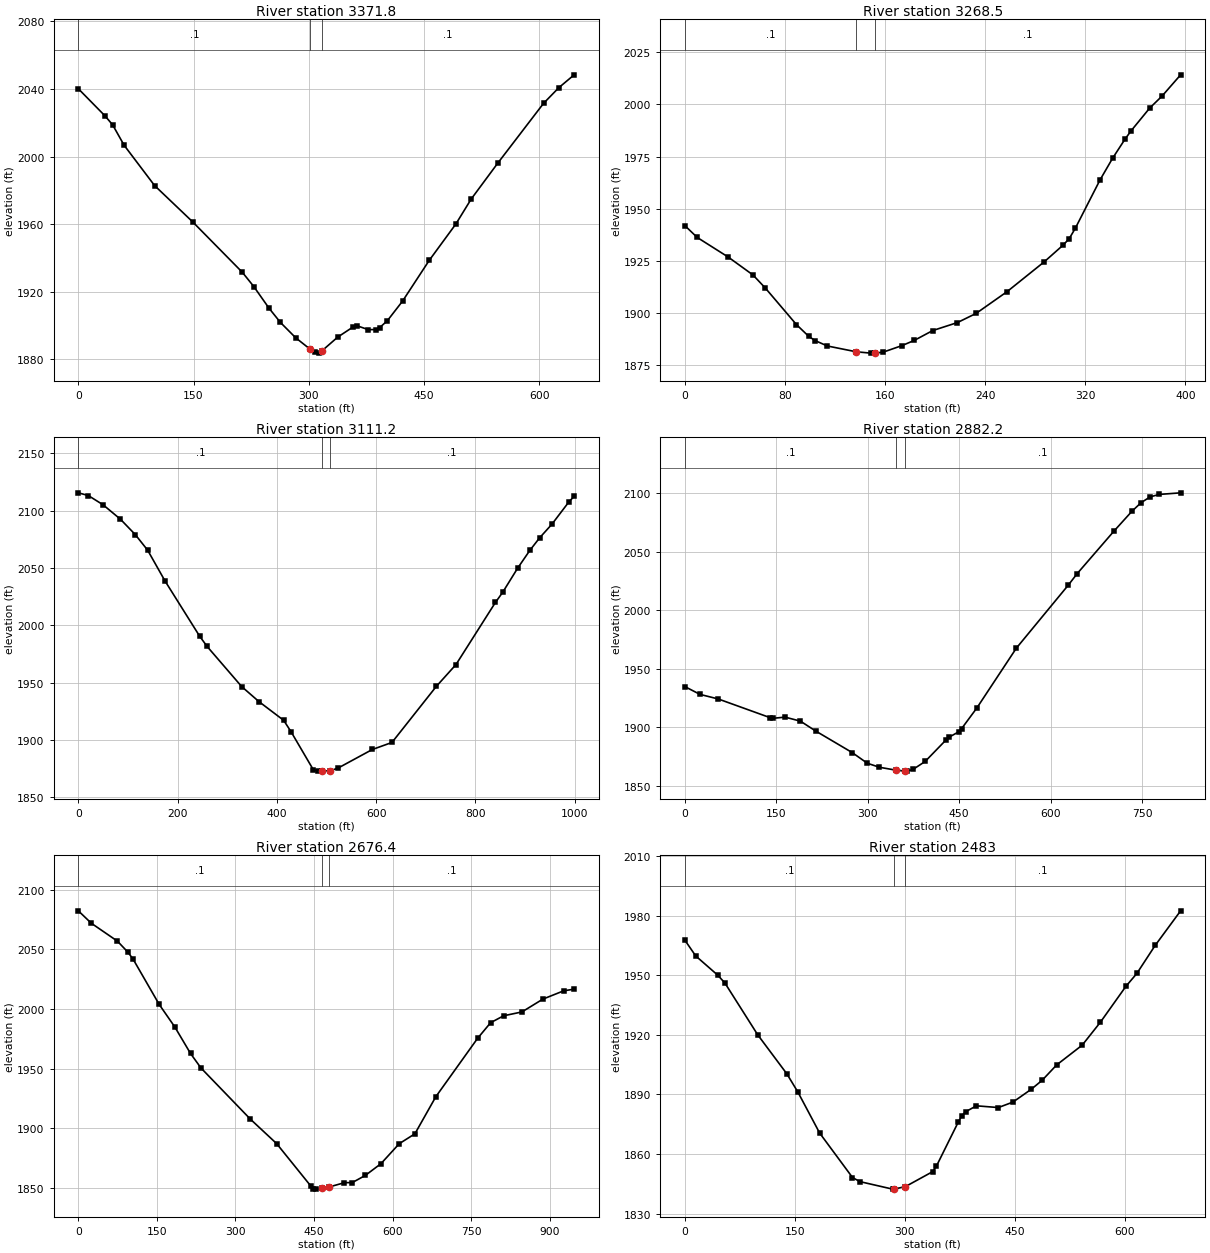
Type RM Length L Ch R = 1 ,3371.8  ,101.5,103.3,105.1
XS GIS Cut Line= 2
     1849058.205      240969.454     1848572.292      240544.279
#Sta/Elev= 30
       0 2040.15    34.8 2024.06    44.7 2018.78    59.6 2006.74    99.3 1982.88
     149 1961.36   213.6 1931.56   228.5 1923.15   248.3 1910.35   263.2  1901.9
   283.1 1892.82   302.2 1885.96   307.9 1884.31   312.9 1883.76   317.2 1885.09
   337.7 1893.21   357.6 1899.18   362.6 1899.99   377.5 1897.67   387.4 1897.68
   392.4 1898.86   402.3 1902.86   422.2 1914.51   456.9 1938.59   491.7 1960.17
   511.6  1974.9   546.3 1996.19   605.9 2031.54   625.8 2040.81   645.7 2048.38
#Mann= 3 , 0 , 0
       0      .1       0   302.2    .045       0   317.2      .1       0
Bank Sta=302.2,317.2
XS Rating Curve= 0 ,0
Exp/Cntr=0.3,0.1

Type RM Length L Ch R = 1 ,3268.5  ,158.9,157.3,155.6
XS GIS Cut Line= 2
     1848998.984      240796.347     1848722.621      240512.391
#Sta/Elev= 30
       0 1941.89     9.9  1936.2    34.7 1926.78    54.5 1918.19    64.4 1911.89
    89.2  1894.4    99.1 1888.72     104 1886.76   113.9 1884.14     137 1881.35
   148.6 1880.71     152 1880.74   158.5 1881.18   173.4 1884.29   183.3 1886.79
   198.1 1891.53   217.9 1895.38   232.8 1899.76   257.6 1910.23   287.3 1924.54
   302.1 1932.41   307.1 1935.54     312 1940.53   331.8 1963.78   341.8 1974.13
   351.7 1983.27   356.6 1987.32   371.5 1998.24   381.4 2004.02   396.2 2014.18
#Mann= 3 , 0 , 0
       0      .1       0     137    .045       0     152      .1       0
Bank Sta=137,152
XS Rating Curve= 0 ,0
Exp/Cntr=0.3,0.1

Type RM Length L Ch R = 1 ,3111.2  ,234.9,229,223.3
XS GIS Cut Line= 3
     1849190.824      241074.908     1849118.944      240697.646
     1848660.311      240287.894
#Sta/Elev= 30
       0  2115.5      20 2113.16    49.9 2105.06    84.8 2092.52   114.7 2079.12
   139.6 2065.56   174.6 2038.74   244.4  1990.6   259.4 1981.67   329.2 1946.64
   364.1 1933.51   413.8 1917.24   428.7 1907.26   473.3 1874.33   483.2 1872.98
   491.8 1873.09   506.8 1873.28   522.9 1875.54   592.4 1891.83     632 1897.97
   721.3  1946.8     761 1965.86   840.4 2019.95   855.2 2028.89     885 2049.69
   909.8 2065.34   929.6 2076.32   954.4 2088.21   989.1 2107.94   999.1 2112.43
#Mann= 3 , 0 , 0
       0      .1       0   491.8    .045       0   506.8      .1       0
Bank Sta=491.8,506.8
XS Rating Curve= 0 ,0
Exp/Cntr=0.3,0.1

Type RM Length L Ch R = 1 ,2882.2  ,207,205.8,204.5
XS GIS Cut Line= 2
     1849412.011       240579.12     1848699.338       240187.69
#Sta/Elev= 30
       0 1934.81    24.9 1928.14    54.9 1924.21   139.7  1908.3   144.7 1907.73
   164.6  1908.7   189.6 1905.28   214.5  1896.9   274.4 1878.49   299.3 1869.34
   319.2 1865.91   346.2 1863.43   361.2 1862.68   364.2 1862.61   374.1 1864.03
   394.1 1870.84     429 1889.57     434 1891.77     449 1896.12   453.9 1898.88
   478.9  1916.5   543.7  1967.6   628.5 2021.17   643.5 2031.26   703.4 2067.31
   733.3 2084.49   748.2  2091.8   763.2 2096.79   778.2 2098.86   813.1 2100.22
#Mann= 3 , 0 , 0
       0      .1       0   346.2    .045       0   361.2      .1       0
Bank Sta=346.2,361.2
XS Rating Curve= 0 ,0
Exp/Cntr=0.3,0.1

Type RM Length L Ch R = 1 ,2676.4  ,192.3,193.4,194.4
XS GIS Cut Line= 3
     1849687.847       240387.34     1849366.119      240319.966
     1848810.455      240049.274
#Sta/Elev= 30
       0 2082.37    24.9 2071.92    74.7  2056.9    94.6  2047.7   104.6  2041.8
   154.4 2003.82   184.3 1984.88   214.2 1962.69   234.1 1950.54   328.7 1907.48
   378.6 1887.06   443.4 1851.73   448.3 1849.31   453.3 1848.84   464.5  1849.8
   479.5 1850.71   508.2 1854.26   523.1 1854.33     548 1860.32   577.9  1870.2
   612.8 1886.97   642.7 1895.26   682.6 1926.35   762.4 1975.38   787.3 1988.51
   812.2 1994.31   847.1 1997.53     887 2008.27   926.9 2015.26   946.8 2016.64
#Mann= 3 , 0 , 0
       0      .1       0   464.5    .045       0   479.5      .1       0
Bank Sta=464.5,479.5
XS Rating Curve= 0 ,0
Exp/Cntr=0.3,0.1

Type RM Length L Ch R = 1 ,2483    ,292.4,294.1,292.6
XS GIS Cut Line= 2
      1849528.09      240209.286     1848934.196      239885.343
#Sta/Elev= 30
       0 1967.71    14.9 1959.71    44.8 1950.08    54.7  1946.1    99.5    1920
   139.3 1900.33   154.2 1891.26     184 1870.55   228.8 1848.18   238.8 1846.12
   283.5 1842.33     286 1842.38     301  1843.6   338.2 1851.13   343.2 1853.82
   373.1 1876.07     378  1879.3     383 1881.25   397.9 1884.27   427.8 1883.39
   447.7 1886.14   472.6 1892.57   487.5 1897.09   507.4 1904.86   542.2  1914.8
   567.1 1926.38   601.9 1944.43   616.8 1950.91   641.7 1964.97   676.5 1982.42
#Mann= 3 , 0 , 0
       0      .1       0     286    .045       0     301      .1       0
Bank Sta=286,301
XS Rating Curve= 0 ,0
Exp/Cntr=0.3,0.1

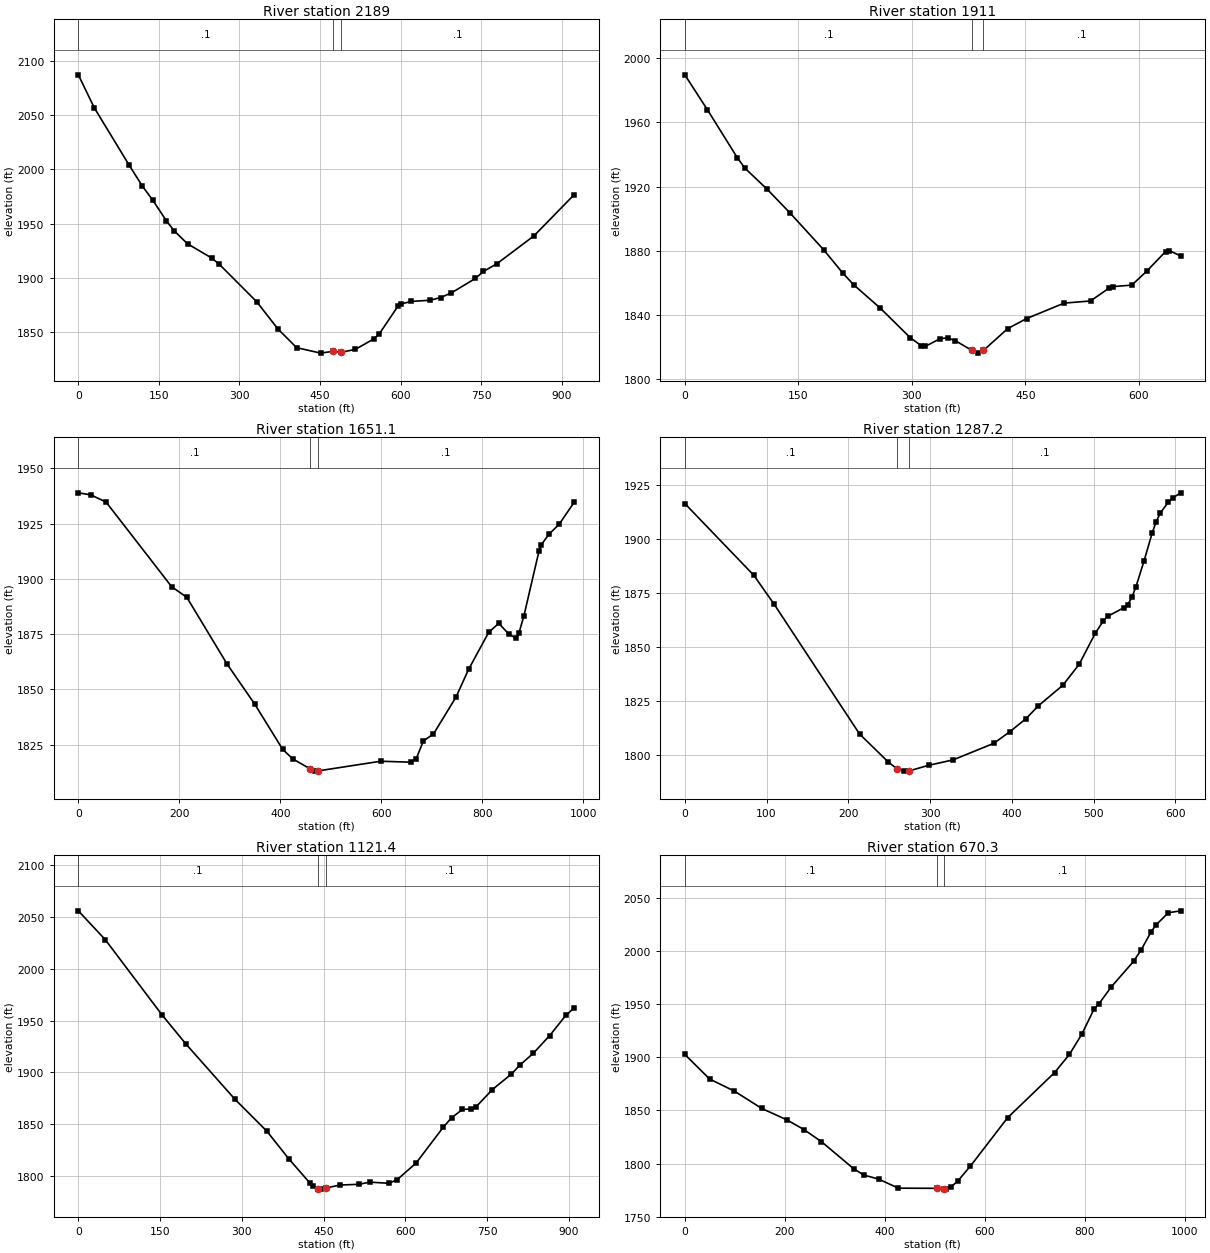
Type RM Length L Ch R = 1 ,2189    ,266.8,278,292.3
XS GIS Cut Line= 3
      1849788.04       240110.22     1849417.077      239819.817
     1849006.182      239631.109
#Sta/Elev= 30
       0 2087.38    29.8 2056.86    94.2 2004.29     119 1984.75   138.8 1971.44
   163.6 1952.81   178.5 1943.29   203.3  1931.3     248 1918.25   262.8 1912.23
   332.3 1877.67   371.9 1852.49   406.6 1835.34   451.3  1830.3     475 1832.03
     490 1831.14   515.8 1833.76   550.6 1843.55   560.6 1848.22   595.3 1873.75
   600.3 1875.67   620.2 1878.08     655 1879.14   674.8 1881.67   694.7 1885.95
   739.4 1899.32   754.3 1905.74   779.2 1912.77   848.7 1938.73   923.3 1976.68
#Mann= 3 , 0 , 0
       0      .1       0     475    .045       0     490      .1       0
Bank Sta=475,490
XS Rating Curve= 0 ,0
Exp/Cntr=0.3,0.1

Type RM Length L Ch R = 1 ,1911    ,274.8,259.9,245
XS GIS Cut Line= 2
     1849784.545      239977.127     1849433.607      239423.725
#Sta/Elev= 30
       0 1989.69    29.8 1967.97    69.5 1937.91    79.4 1931.47   109.2 1918.13
     139 1903.51   183.7 1880.42   208.5 1866.14   223.4 1858.57   258.2 1844.16
   297.9 1825.69   312.8 1820.56   317.7 1820.19   337.6  1825.1   347.5 1825.47
   357.4 1823.82   379.6 1817.68   387.2 1816.02   394.6 1817.66   426.9 1831.36
   451.8  1837.6   501.4 1847.24   536.2 1848.56     561 1856.69   565.9 1857.54
   590.8 1858.46   610.6 1867.22   635.4 1879.41   640.4 1879.95   655.3  1876.7
#Mann= 3 , 0 , 0
       0      .1       0   379.6    .045       0   394.6      .1       0
Bank Sta=379.6,394.6
XS Rating Curve= 0 ,0
Exp/Cntr=0.3,0.1

Type RM Length L Ch R = 1 ,1651.1  ,370.4,363.9,357.4
XS GIS Cut Line= 3
     1850254.582      239621.779       1849820.1      239554.978
     1849312.346      239365.054
#Sta/Elev= 30
       0 1938.92      25 1937.97      55 1934.72   184.8 1896.42   214.8 1891.61
   294.7 1861.35   349.7 1843.12   404.6 1822.79   424.6 1818.49   459.3 1813.94
   469.4 1812.95   474.3 1813.04   598.7 1817.43   658.4 1816.99   668.4 1818.23
   683.3 1826.65   703.2 1829.76   747.9 1846.53   772.8 1859.06   812.6 1875.82
   832.5 1879.84   852.4 1874.97   867.3 1873.06   872.3 1875.39   882.2 1883.22
   912.1 1912.58     917 1915.53     932 1920.24   951.9 1924.65   981.7 1934.64
#Mann= 3 , 0 , 0
       0      .1       0   459.3    .045       0   474.3      .1       0
Bank Sta=459.3,474.3
XS Rating Curve= 0 ,0
Exp/Cntr=0.3,0.1

Type RM Length L Ch R = 1 ,1287.2  ,167.8,165.7,163.7
XS GIS Cut Line= 2
     1850054.497      239221.261     1849449.804       239175.37
#Sta/Elev= 30
       0 1916.28    84.5 1882.98   109.4 1869.54   213.7 1809.52   248.5 1796.66
   259.3 1793.42   268.4  1792.3   274.3 1792.41   298.2 1794.99   328.1 1797.51
   377.8 1805.16   397.7  1810.6   417.5 1816.68   432.5 1822.58   462.3 1832.08
   482.2 1841.72     502 1856.16     512 1861.99     517 1863.98   536.8 1867.99
   541.8 1869.49   546.8 1872.82   551.8 1877.76   561.7 1889.72   571.6 1902.65
   576.6 1907.94   581.6 1911.93   591.5 1916.95   596.5  1918.8   606.4 1921.23
#Mann= 3 , 0 , 0
       0      .1       0   259.3    .045       0   274.3      .1       0
Bank Sta=259.3,274.3
XS Rating Curve= 0 ,0
Exp/Cntr=0.3,0.1

Type RM Length L Ch R = 1 ,1121.4  ,452,451.2,450.3
XS GIS Cut Line= 3
       1850261.9      239034.785     1849806.925      239039.525
     1849351.949      239044.265
#Sta/Elev= 30
       0 2056.02    49.5 2028.12   153.3 1955.65   197.8 1927.12   286.8  1874.3
   346.2 1843.01   385.8 1816.67   425.3 1792.85   430.3 1789.96   439.1 1787.59
   445.1 1787.12   454.1 1788.18     480 1791.04     515  1791.8     535 1793.87
     570 1792.77     585 1796.19     620 1812.37     670 1847.08     685 1856.06
     705 1864.12     720 1864.54     730 1866.66     760 1883.36     795 1898.36
     810 1906.79     835 1918.34     865 1935.45     895  1955.2     910 1962.17
#Mann= 3 , 0 , 0
       0      .1       0   439.1    .045       0   454.1      .1       0
Bank Sta=439.1,454.1
XS Rating Curve= 0 ,0
Exp/Cntr=0.3,0.1

Type RM Length L Ch R = 1 ,670.3   ,230.3,243.3,256.2
XS GIS Cut Line= 3
     1850226.878      238584.635     1849607.488      238628.343
     1849237.563      238654.753
#Sta/Elev= 30
       0 1902.63    49.7 1879.44    99.4 1868.04     154 1851.75   203.7 1841.18
   238.4  1831.9   273.2  1820.6   337.8 1795.11   357.7 1789.22   387.5  1785.4
   427.2 1776.82   504.2 1776.68   519.2 1776.01   521.6 1775.92   531.5 1777.51
   546.4 1783.76   571.3 1797.55   645.7 1843.05   739.6  1885.5   769.3 1902.54
     794 1921.48   818.7 1945.32   828.6 1950.32   853.3 1966.24   897.8  1990.2
   912.7 2000.82   932.5  2017.6   942.4 2024.26   967.1  2035.8   991.8 2037.64
#Mann= 3 , 0 , 0
       0      .1       0   504.2    .045       0   519.2      .1       0
Bank Sta=504.2,519.2
XS Rating Curve= 0 ,0
Exp/Cntr=0.3,0.1

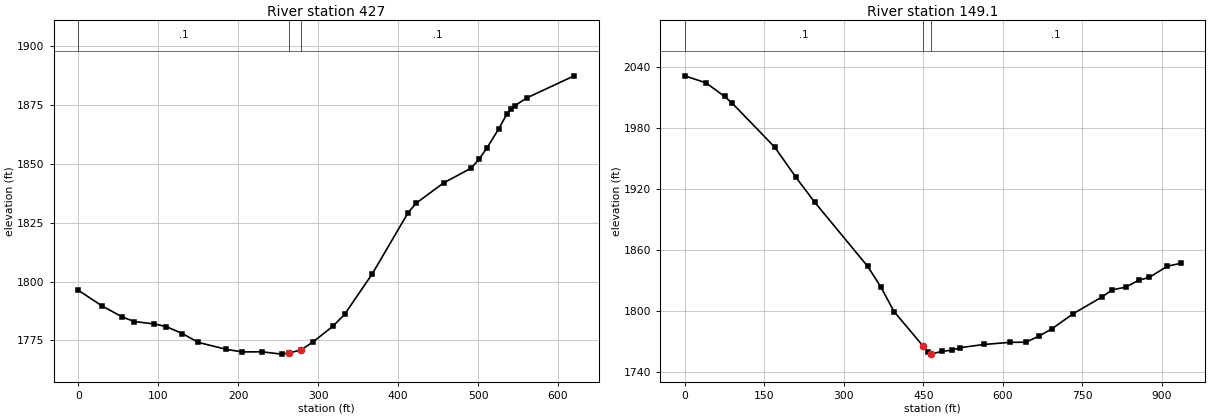
Type RM Length L Ch R = 1 ,427     ,284.3,277.9,271.2
XS GIS Cut Line= 4
     1849895.185      238599.241     1849786.789      238419.431
      1849694.97      238372.247     1849391.461      238418.156
#Sta/Elev= 30
       0 1796.28      30 1789.55      55 1784.95      70    1783      95    1782
     110 1780.84     130 1777.92     150 1774.15     185 1771.21     205  1770.1
   229.6 1770.16   254.2 1769.17   263.5 1769.66   278.5 1770.93   293.5 1774.33
   318.1 1780.92     333 1786.02   367.6  1803.2   412.2 1829.06   422.1 1833.12
   456.8 1841.83   491.4 1848.12   501.3 1851.95   511.2 1856.74   526.1 1864.94
     536 1871.06   540.9 1873.22   545.9 1874.61   560.7  1877.9   620.2 1887.31
#Mann= 3 , 0 , 0
       0      .1       0   263.5    .045       0   278.5      .1       0
Bank Sta=263.5,278.5
XS Rating Curve= 0 ,0
Exp/Cntr=0.3,0.1

Type RM Length L Ch R = 1 ,149.1   ,147.7,149.1,150.5
XS GIS Cut Line= 3
     1850360.872      238393.688     1849858.234      238261.989
     1849451.429      238347.431
#Sta/Elev= 30
       0 2030.91      40 2024.01    74.9 2010.73    89.9 2003.82   169.9 1960.77
   209.8 1931.27   244.8 1907.11   344.7 1844.17   369.7 1823.93   394.7 1799.69
   449.3 1765.95   459.6 1759.73   464.3 1758.08   464.6 1757.95   484.6 1760.67
   504.6 1761.85   519.6 1764.27   564.1 1767.41   613.6  1769.5   643.3 1769.65
   668.1 1775.59   692.8 1782.86   732.4 1797.52   786.8 1813.96   806.6 1821.08
   831.4 1823.56   856.1 1830.43   875.9 1833.15   910.5 1844.19   935.3 1847.02
#Mann= 3 , 0 , 0
       0      .1       0   449.3    .045       0   464.3      .1       0
Bank Sta=449.3,464.3
XS Rating Curve= 0 ,0
Exp/Cntr=0.3,0.1

Chan Stop Cuts=-1
Use User Specified Reach Order=0